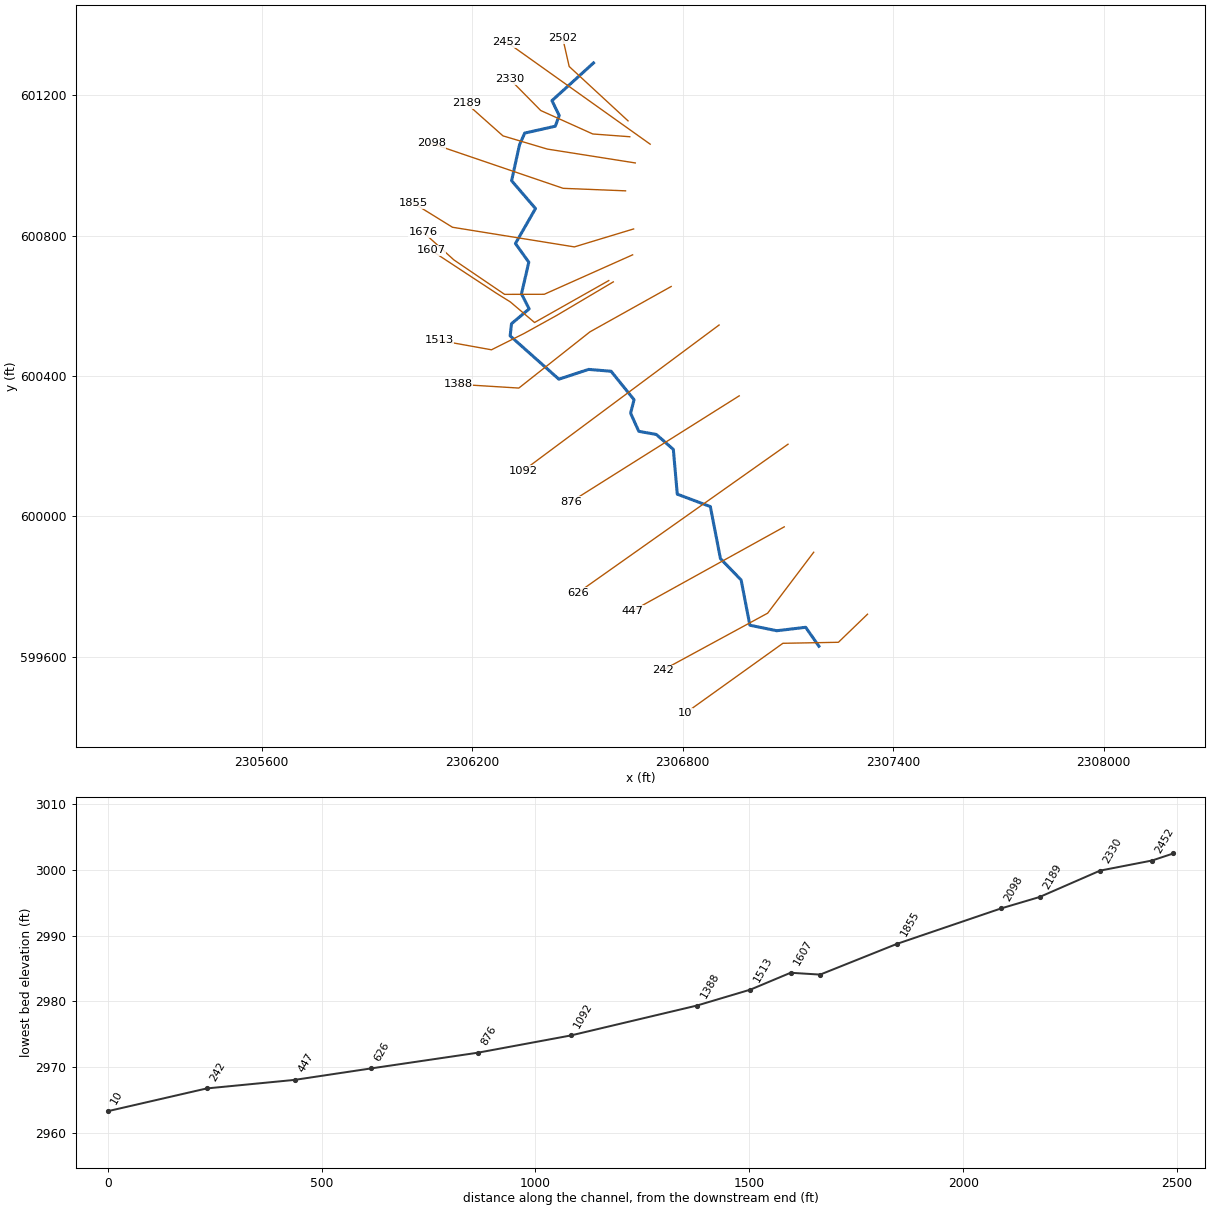
--- OLDRDRNT1.prj (project) ---

Proj Title=OLDRDRNT1
Current Plan=p01
Default Exp/Contr=0,0
English Units
Geom File=g01
Flow File=f01
Plan File=p01
Background Map Layer=Inundation Boundary (01pct Value_0)
BEGIN DESCRIPTION:
----------MODEL BY WOOD PLC 2021----------
Stream Name: Old Road Run Tributary 1
Flood Zone: Enhanced Approximate
Pocahontas County, WV
HEC-RAS Version: RAS 6.1
Vertical Datum: NAVD88
Projection: NAD 1983 StatePlane West Virginia S FIPS 4702 (US Feet)
Terrain: 1-meter LIDAR (FEMA Region III 3DEP collected 2016-2018)
Land Use: 2019 NLCD
Hydrologic Method:
WV SIR2010-5033 regression equations
Hydraulic considerations- XS 1607 was added to fix the gap in the floodplain
END DESCRIPTION:
DSS Export Rating Curves= 0
DSS Export Rating Curve Sorted= 0
DSS Export Volume Flow Curves= 0
DXF OffsetX= 0
DXF OffsetY= 0
DXF ScaleX= 0
DXF ScaleY= 0

--- OLDRDRNT1.p01 (plan) ---

Plan Title=Floodplain
Program Version=6.10
Short Identifier=Floodplain
Geom File=g01
Flow File=f01
Subcritical Flow
K Sum by GR= 0
Std Step Tol= 0.01
Critical Tol= 0.01
Num of Std Step Trials= 20
Max Error Tol= 0.3
Flow Tol Ratio= 0.001
Split Flow NTrial= 30
Split Flow Tol= 0.02
Split Flow Ratio= 0.02
Log Output Level= 0
Friction Slope Method= 1
Unsteady Friction Slope Method= 2
Unsteady Bridges Friction Slope Method= 1
Parabolic Critical Depth
Global Vel Dist= 0 , 0 , 0
Global Log Level= 0
CheckData=True
Encroach Param=-1 ,0,0, 0
Mapping Interval=1HOUR
Computation Time Step Use Courant=        0
Computation Time Step Use Time Series=    0
Computation Time Step Count To Double=0
Computation Time Step Max Doubling=0
Computation Time Step Max Halving=0
Computation Time Step Residence Courant=0
Run HTab= 0
Run UNet= 0
Run Sediment= 0
Run PostProcess= 0
Run WQNet= 0
Run RASMapper=-1
UNET Theta= 0
UNET Theta Warmup= 0
UNET ZTol= 0
UNET ZSATol= 0
UNET MxIter= 0
UNET Max Iter WO Improvement= 0
UNET MaxInSteps= 0
UNET DtIC= 0
UNET DtMin= 0
UNET MaxCRTS= 0
UNET WFStab= 0
UNET SFStab= 0
UNET WFX= 1
UNET SFX= 1
UNET Gravity=32.174
UNET 1D Methodology=Finite Difference
UNET DSS MLevel= 1
UNET Pardiso=0
UNET DZMax Abort= 0
UNET Use Existing IB Tables= 0
UNET Froude Reduction=False
UNET Froude Limit= 0
UNET Froude Power= 0
UNET D1 Cores= 0
UNET WindReference=Eulerian
UNET WindDragFormulation=Hsu (1988)
UNET D2 Coriolis=0
UNET D2 Cores= 0
UNET D2 Theta= 1
UNET D2 Theta Warmup= 1
UNET D2 Z Tol= 0.01
UNET D2 Volume Tol= 0.01
UNET D2 Max Iterations= 20
UNET D2 Equation= 0
UNET D2 RampUpFraction=0.1
UNET D2 TimeSlices= 1
UNET D2 Turbulence Formulation=Non-Conservative (original)
UNET D2 Eddy Viscosity=0.3
UNET D2 Transverse Eddy Viscosity=0.1
UNET D2 Smagorinsky Mixing=0
UNET D2 BCVolumeCheck=0
UNET D2 Cores=0
UNET D2 SolverType=PARDISO (Direct)
UNET D2 Minimum Iterations= 2147483647
UNET D2 Maximum Iterations= 2147483647
UNET D2 Restart Number= 10
UNET D2 Relaxation Coeff=1.3
UNET D2 SOR Precondition Iterations= 10
UNET D2 ILUT Maximum Fill= 8
UNET D2 ILUT Tolerance=1E-08
UNET D1D2 MaxIter= 0
UNET D1D2 ZTol=0.01
UNET D1D2 QTol=0.1
UNET D1D2 MinQTol=1
Write IC File= 0
Write IC File at Fixed DateTime=0
Write IC File at Sim End=0
Echo Input=False
Echo Parameters=False
Echo Output=False
Write Detailed= 0
HDF Write Warmup=0
HDF Write Time Slices=0
HDF Flush=0
HDF Compression= 1
HDF Chunk Size= 1
HDF Spatial Parts= 1
HDF Use Max Rows=0
HDF Fixed Rows= 1
Calibration Method= 0
Calibration Iterations= 20
Calibration Max Change=0.05
Calibration Tolerance=0.2
Calibration Maximum=1.5
Calibration Minimum=0.5
Calibration Optimization Method= 1
WQ AD Non Conservative
WQ ULTIMATE=-1
WQ Max Comp Step=1HOUR
WQ Output Interval=15MIN
WQ Output Selected Increments= 0
WQ Output face flow=0
WQ Output face velocity=0
WQ Output face area=0
WQ Output face dispersion=0
WQ Output cell volume=0
WQ Output cell surface area=0
WQ Output cell continuity=0
WQ Output cumulative cell continuity=0
WQ Output face conc=0
WQ Output face dconc_dx=0
WQ Output face courant=0
WQ Output face peclet=0
WQ Output face adv mass=0
WQ Output face disp mass=0
WQ Output cell mass=0
WQ Output cell source sink temp=0
WQ Output nsm pathways=0
WQ Output nsm derived pathways=0
WQ Create Restart=0
WQ Fixed Restart=0
WQ System Summary=0
WQ Write To DSS=0
Sorting and Armoring Iterations= 10
XS Update Threshold= 0.02
Bed Roughness Predictor= 0
Hydraulics Update Threshold= 0.02
Energy Slope Method= 1
Volume Change Method= 1
Sediment Retention Method= 0
Sediment TS Multiplier= 1
Warm Up Method= 0
XS Weighting Method= 0
Number of US Weighted Cross Sections= 1
Number of DS Weighted Cross Sections= 1
Upstream XS Weight=0
Main XS Weight=1
Downstream XS Weight=0
Number of DS XS's Weighted with US Boundary= 1
Upstream Boundary Weight= 1
Weight of XSs Associated with US Boundary= 0
Number of US XS's Weighted with DS Boundary= 1
Downstream Boundary Weight= 0.5
Weight of XSs Associated with DS Boundary= 0.5
Percentile Method= 0
Sediment Output Level= 3
Mass or Volume Output= 0
Output Increment Type= 1
Profile and TS Output Increment= 1
Transport Output Increment 1
XS Output Flag= 0
XS Output Increment= 10
Read HDF5 Sediment Hotstart= 0
Sediment Hotstart Type= 0
Write Gradation File= 0
Read Gradation Hotstart= 0
Write HDF5 File= 1
Write Binary Output= 1
Write DSS Sediment File= 0
DSS Sediment Output Type= 1
SV Curve= 0
Specific Gage Flag= 0
Subcell Erosion Methods= 0
Subcell Deposition Methods= 0
Advection Scheme= 1
Matrix Solver= 0
Implicit Weighting Factor= 1
Maximum Outer Loop Convergence Iterations= 5
Convergence Maximum Absolute= 0.001
Convergence RMSE= 0.0001
Grain Fractions Max Abs Error= 0.001
Max Subgrid Regions= 1
Max Subgrid Length Scale= 3.402823E+38
Initial Layer Thickness= 3.402823E+38
Min Layer Thickness= 3.402823E+38
Max Layer Thickness= 3.402823E+38
Number of Layers= 5

--- OLDRDRNT1.f01 (steady flow) ---

Flow Title=Flow
Program Version=6.10
Number of Profiles= 6
Profile Names=01pct,10pct,04pct,02pct,0_2pct,01plus
River Rch & RM=OLDRDRNT1,Main            ,2502
     160    80.4     110     134     229     236
River Rch & RM=OLDRDRNT1,Main            ,2098
     293     151     203     246     414     433
River Rch & RM=OLDRDRNT1,Main            ,1513
     375     195     261     316     528     554
Boundary for River Rch & Prof#=OLDRDRNT1,Main            , 1
Up Type= 0
Dn Type= 3
Dn Slope=0.01108
Boundary for River Rch & Prof#=OLDRDRNT1,Main            , 2
Up Type= 0
Dn Type= 3
Dn Slope=0.01108
Boundary for River Rch & Prof#=OLDRDRNT1,Main            , 3
Up Type= 0
Dn Type= 3
Dn Slope=0.01108
Boundary for River Rch & Prof#=OLDRDRNT1,Main            , 4
Up Type= 0
Dn Type= 3
Dn Slope=0.01108
Boundary for River Rch & Prof#=OLDRDRNT1,Main            , 5
Up Type= 0
Dn Type= 3
Dn Slope=0.01108
Boundary for River Rch & Prof#=OLDRDRNT1,Main            , 6
Up Type= 0
Dn Type= 3
Dn Slope=0.01108
DSS Import GetInterval= 0
DSS Import GetPeak= 0
DSS Import FillOption= 0

--- OLDRDRNT1.g01 (geometry) ---

Geom Title=Geometry
Program Version=6.10

River Reach=OLDRDRNT1       ,Main
Reach XY= 30
2306545.98772048601291.7925277482306427.51055286601184.376301821
2306448.28905144601141.9338839682306437.04122288601111.512792272
 2306349.8817083601091.836570284 2306335.1245418601058.632945679
2306312.52763062600956.2551031492306380.62580515 600876.93533326
     2306323.473      600777.1112306361.55928798600723.941431971
2306340.71255649600633.7316955752306362.51975773600590.960244996
2306312.29927552600548.6256236252306308.42551931600513.900166226
     2306447.229      600390.506     2306532.024      600418.386
2306596.07048672600413.115773395     2306661.497      600331.991
     2306651.681      600293.6312306674.99786873600241.904152148
2306725.08000251600232.911503818      2306773.49      600190.323
     2306784.716        600062.8     2306878.948      600027.448
     2306907.793      599879.028     2306966.684      599818.291
2306991.60165156599689.3233344112307068.18412343599673.568777662
2307150.63979119599683.391516608     2307188.397      599629.494

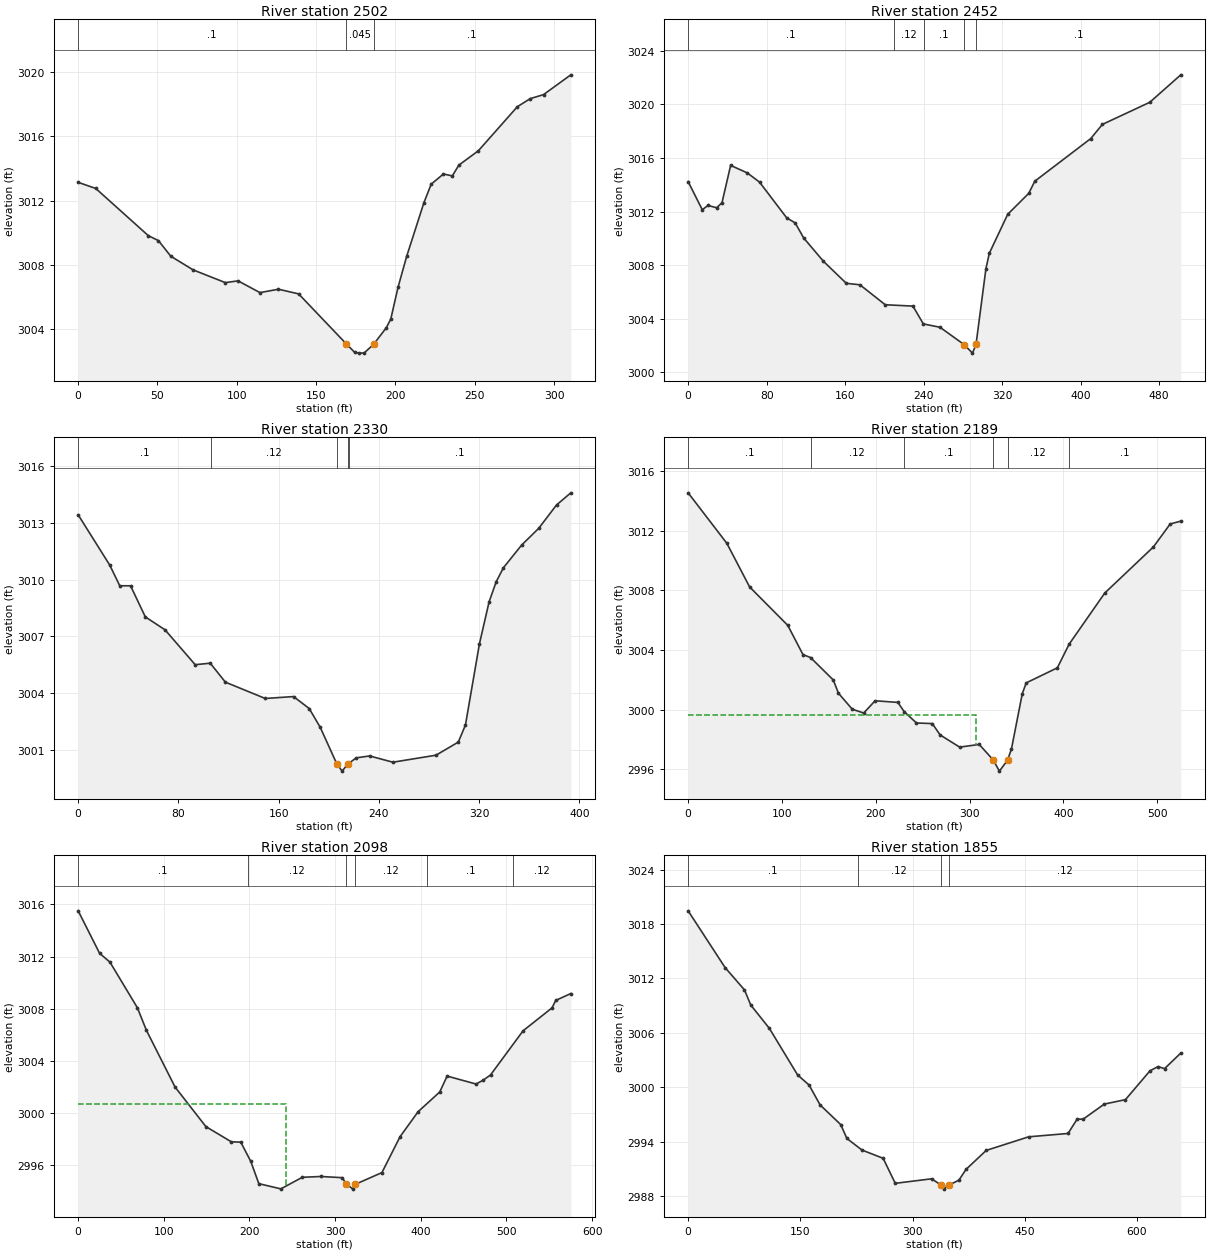
Type RM Length L Ch R = 1 ,2502    ,47.7,49.8,45.5
XS GIS Cut Line= 3
2306644.31711672601126.8180966072306476.62434094601281.751639447
2306458.39686531601361.952532212
#Sta/Elev= 30
       0 3013.13    11.1 3012.75    44.2 3009.82    50.6 3009.51    58.4 3008.54
    72.5 3007.69    92.8  3006.9   100.8 3007.01   114.6 3006.28   126.3 3006.49
     139  3006.2     169  3003.1   174.4 3002.56   177.3 3002.52   180.3 3002.53
   186.2 3003.06   194.3  3004.1   197.1 3004.64   201.7 3006.62   207.1 3008.53
     218 3011.87   222.6 3013.02   230.3 3013.65   235.9 3013.53     240  3014.2
   252.3 3015.09   276.9 3017.83     285 3018.33   293.4 3018.58   310.6 3019.81
#Mann= 3 ,0,0
       0      .1       0     169    .045       0   186.2      .1       0
Bank Sta=169,186.2
XS Rating Curve= 0 ,0
Exp/Cntr(USF)=0,0
Exp/Cntr=0.3,0.1

Type RM Length L Ch R = 1 ,2452    ,118.5,121.7,123.6
XS GIS Cut Line= 2
     2306707.459      601060.318     2306298.382      601351.525
#Sta/Elev= 30
       0 3014.24    14.4 3012.14    20.2 3012.46    29.1 3012.29    34.5 3012.67
    43.3 3015.45    60.3 3014.89    72.8  3014.2   100.5 3011.53   109.1 3011.16
   117.7 3010.04   137.8  3008.3   161.2 3006.65   175.1 3006.54   200.9 3005.05
   229.1 3004.95   239.7 3003.62   256.7 3003.37   281.2 3002.08   289.8 3001.44
   293.43002.088   303.5 3007.74     307  3008.9   325.7  3011.8   347.2 3013.37
   353.3 3014.27   410.3 3017.45   422.2 3018.51   470.5 3020.16   502.1 3022.21
#Mann= 5 ,-1,0
       0      .1       0     210     .12       0     240      .1       0
   281.2    .045       0   293.4      .1       0
Bank Sta=281.2,293.4
XS Rating Curve= 0 ,0
Exp/Cntr=0.3,0.1

Type RM Length L Ch R = 1 ,2330    ,136.9,141.5,145.9
XS GIS Cut Line= 4
2306649.30879134601081.4946217432306543.81890253601089.385597677
2306395.55161787601156.2512358592306307.92025354601245.128543752
#Sta/Elev= 30
       0 3013.41    25.2 3010.76    33.2 3009.67    41.8 3009.67    53.6 3008.03
    69.3 3007.35    93.4 3005.51   105.4 3005.59   117.5 3004.59   149.3 3003.73
   171.9 3003.83   184.4  3003.2   193.2 3002.21   206.3  3000.3   210.7  2999.9
   215.1 3000.27     222  3000.6   232.6  3000.7   251.2 3000.37   285.6 3000.74
   303.4 3001.43   309.1 3002.33   320.3 3006.62     328 3008.83   333.7 3009.89
   339.4 3010.62     354 3011.82   367.6  3012.7   381.8 3013.93   393.2 3014.57
#Mann= 5 ,-1,0
       0      .1       0  105.78     .12       0   206.3    .045       0
   215.1     .12       0  215.78      .1       0
Bank Sta=206.3,215.1
XS Rating Curve= 0 ,0
Exp/Cntr(USF)=0,0
Exp/Cntr=0.3,0.1

Type RM Length L Ch R = 1 ,2189    ,90.4,90.2,90.7
XS GIS Cut Line= 4
2306665.06510064601006.8241085232306414.21724641601046.380885536
2306287.82851986 601084.008063672306183.63018041601176.628809846
#Sta/Elev= 30
       0 3014.55    41.3 3011.16    65.5 3008.24   106.2 3005.66   122.4  3003.7
   130.5  3003.5   154.8 3001.99   160.2 3001.11     175 3000.03   187.2 2999.78
   199.3  3000.6   223.6 3000.49   230.2 2999.88   243.4 2999.11   260.3 2999.07
   268.6 2998.31   289.5 2997.49   310.3 2997.67   325.4 2996.62   331.8 2995.88
   340.5 2996.61   344.7 2997.37   356.2 3001.07   360.4  3001.8   393.6 3002.81
   406.2  3004.4   444.2 3007.83     496 3010.92   513.9 3012.46   525.2 3012.65
#Mann= 6 ,-1,0
       0      .1       0   130.5     .12       0   230.2      .1       0
   325.4    .045       0   340.5     .12       0   406.2      .1       0
#XS Ineff= 2 , 0
          306.98 2999.66
Permanent Ineff=
       F       F
Bank Sta=325.4,340.5
XS Rating Curve= 0 ,0
Exp/Cntr(USF)=0,0
Exp/Cntr=0.3,0.1

Type RM Length L Ch R = 1 ,2098    ,238.8,243.1,242.6
XS GIS Cut Line= 3
2306637.20238711600927.3211725272306459.56282006600934.464150573
     2306083.444      601062.629
#Sta/Elev= 30
       0 3015.51      25 3012.25    37.1 3011.57    69.1 3008.07    79.7 3006.33
   113.1 3001.98   149.1 2998.94   178.9 2997.77   189.8 2997.75   201.5 2996.27
   210.9 2994.56   236.6 2994.16   261.7 2995.05   283.5 2995.11   308.1 2995.02
   313.2 2994.53   320.8 2994.14   323.2  2994.5   354.6 2995.41   375.8 2998.17
   396.9 3000.09   422.1  3001.6   430.7 3002.82   464.5 3002.21   472.9 3002.51
   481.4 3002.91   519.4  3006.3   553.2 3008.06   557.5 3008.63   575.1 3009.16
#Mann= 6 ,-1,0
       0      .1       0  197.78     .12       0   313.2    .045       0
   323.2     .12       0  407.78      .1       0  507.78     .12       0
#XS Ineff= 2 , 0
          243.19  3000.7
Permanent Ineff=
       F       F
Bank Sta=313.2,323.2
XS Rating Curve= 0 ,0
Exp/Cntr=0.3,0.1

Type RM Length L Ch R = 1 ,1855    ,178.4,179.7,179.9
XS GIS Cut Line= 4
2306660.24110344600818.6882178522306491.40120156600767.553847567
 2306144.0734034600823.5122150492306033.12146788600892.012975242
#Sta/Elev= 30
       0 3019.45    49.4 3013.19    75.3 3010.73    83.7 3009.06   108.7 3006.47
   146.3 3001.35   161.7 3000.23   176.4 2998.04     204 2995.87   212.2 2994.34
   232.4 2993.06   260.7 2992.15   276.9 2989.39   325.5 2989.89   337.7 2989.22
   341.7 2988.75   348.1 2989.17     362 2989.74   371.5 2990.93   398.5 2993.02
   455.2 2994.52   507.9 2994.89     520 2996.47   528.1 2996.47   556.3 2998.13
   584.6 2998.62   617.4  3001.8   628.2 3002.27   636.9 3002.04   658.6 3003.76
#Mann= 4 ,-1,0
       0      .1       0  226.41     .12       0   337.7    .045       0
   348.1     .12       0
Bank Sta=337.7,348.1
XS Rating Curve= 0 ,0
Exp/Cntr(USF)=0,0
Exp/Cntr=0.3,0.1

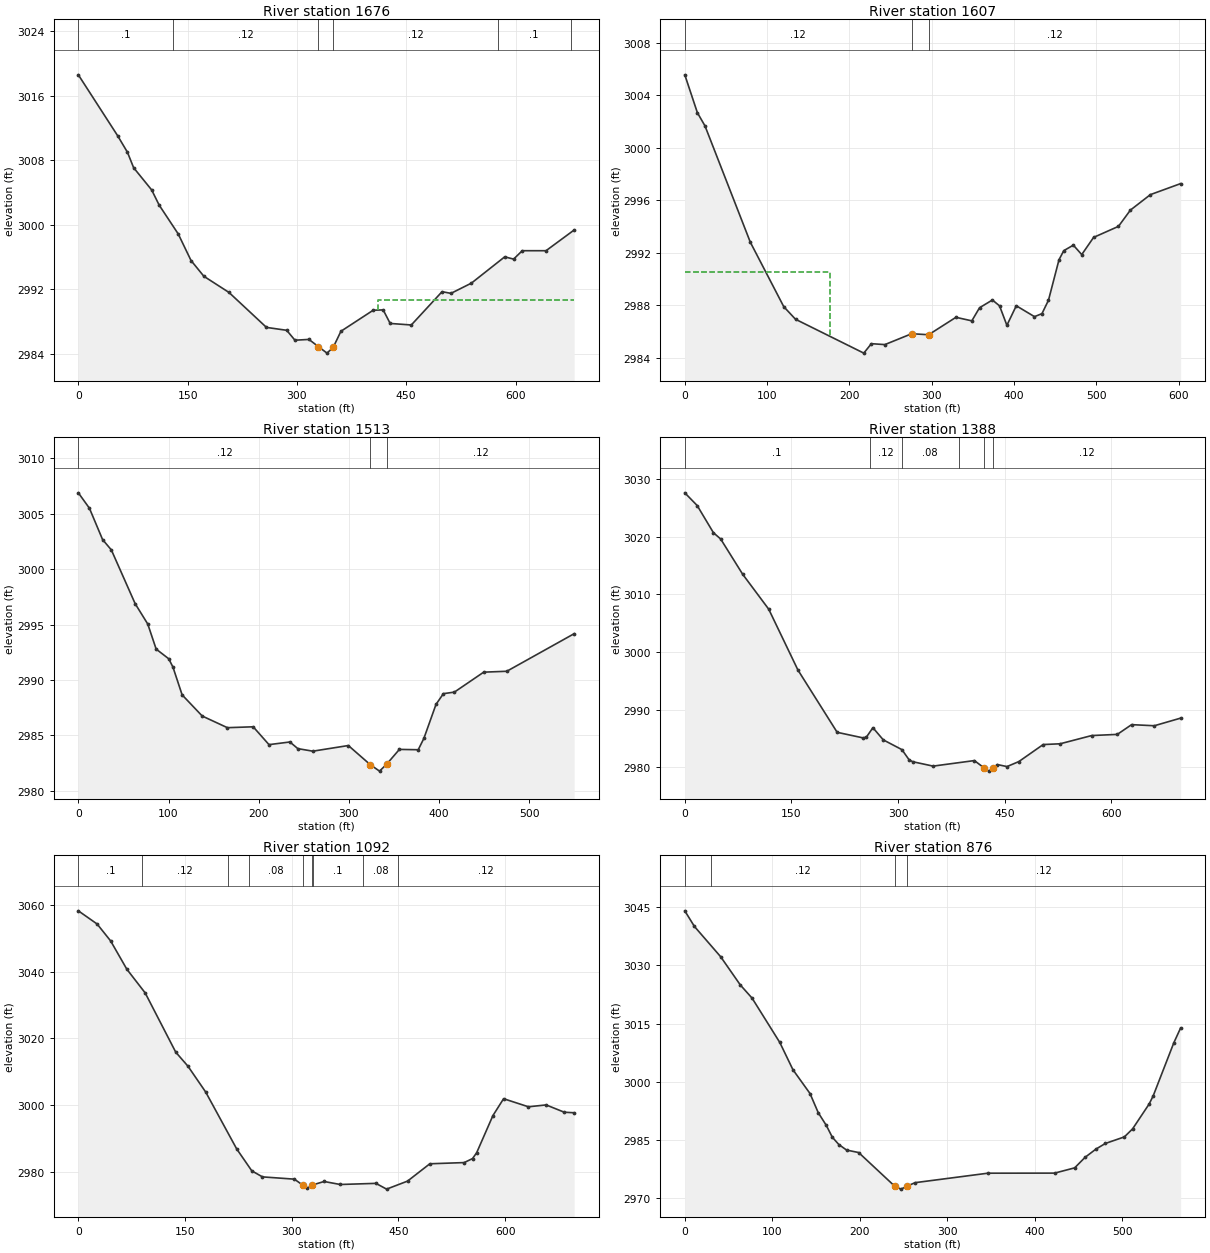
Type RM Length L Ch R = 1 ,1676    ,73.7,69,58
XS GIS Cut Line= 5
2306657.47549083600744.9252342012306405.53405146 600632.48192606
2306292.62701625600632.2646927622306148.24126182600730.351924872
2306061.38983028600808.922238529
#Sta/Elev= 30
       0 3018.58      54 3011.02    67.4 3008.98    75.9 3007.06   100.7  3004.3
   110.9 3002.43   137.1 2998.85   154.7 2995.55   172.3  2993.6   206.7  2991.6
   258.2 2987.26     286  2986.9   297.3 2985.67   316.5 2985.77   329.32984.887
   341.3 2984.07   349.9  2984.8   360.4 2986.78   404.7 2989.39   418.4 2989.43
     428 2987.75     457 2987.56   499.2 2991.69   511.4 2991.48   539.5 2992.75
   585.2 2996.01   597.4 2995.73   609.3 2996.77   641.9 2996.77   680.5 2999.34
#Mann= 6 ,-1,0
       0      .1       0     130     .12       0   329.3    .045       0
   349.9     .12       0  575.53      .1       0  675.53     .12       0
#XS Ineff= 2 , 0
                          410.93         2990.65
Permanent Ineff=
       F       F
Bank Sta=329.3,349.9
XS Rating Curve= 0 ,0
Exp/Cntr=0.3,0.1

Type RM Length L Ch R = 1 ,1607    ,79.3,94.1,111.4
XS GIS Cut Line= 5
  2306589.505546600671.5641310412306377.93574902600552.060249292
 2306308.9922189600610.6658113292306268.75753092600635.740326759
2306083.80672742600757.374638971
#Sta/Elev= 30
       0 3005.56    15.3 3002.67    24.5 3001.67    79.6  2992.8   120.2 2987.89
   134.5 2986.93   217.4 2984.35   226.6 2985.07     243    2985   275.6 2985.83
   296.1 2985.75   329.3 2987.08   348.6 2986.81     358 2987.81   373.6  2988.4
   382.3 2987.95   391.2 2986.47   402.6 2987.96   424.7 2987.13   433.8 2987.36
   441.7 2988.38   454.5 2991.47   460.3 2992.16   471.9 2992.58   482.1 2991.86
   496.5 2993.17   526.7 2994.01   541.2 2995.25   565.5 2996.43   602.2 2997.27
#Mann= 3 ,-1,0
       0     .12       0   275.6    .045       0   296.1     .12       0
#XS Ineff= 2 , 0
          176.74 2990.52
Permanent Ineff=
       F       F
Bank Sta=275.6,296.1
XS Rating Curve= 0 ,0
Exp/Cntr(USF)=0,0
Exp/Cntr=0.3,0.1

Type RM Length L Ch R = 1 ,1513    ,121.5,124.8,128.9
XS GIS Cut Line= 5
2306602.40687641600667.8310197582306441.36889743600572.404773402
2306347.93255567600520.7133751442306255.13684656600474.284976974
2306105.48142583600501.269202311
#Sta/Elev= 30
       0 3006.89    12.3  3005.5    26.9 3002.67    36.6 3001.74      63 2996.89
      77 2995.05    86.3 2992.79   100.2 2991.92   104.9 2991.17   115.1 2988.66
   137.4 2986.75   165.3  2985.7   193.9 2985.78   211.4 2984.17   234.6 2984.41
   243.4 2983.81     260 2983.58   299.4 2984.09   323.9 2982.35     334 2981.78
   341.92982.406     356 2983.74   376.9 2983.71   383.2 2984.74   396.6  2987.8
   404.8 2988.77     417 2988.91   449.5 2990.71   475.1 2990.79   549.8 2994.18
#Mann= 3 ,-1,0
       0     .12       0   323.9    .045       0   341.9     .12       0
Bank Sta=323.9,341.9
XS Rating Curve= 0 ,0
Exp/Cntr(USF)=0,0
Exp/Cntr=0.3,0.1

Type RM Length L Ch R = 1 ,1388    ,294.4,295.3,291.9
XS GIS Cut Line= 4
2306767.33384121600654.6723131652306535.78197577600525.389188294
2306333.17409351600365.2324813652306159.28785382600375.981591168
#Sta/Elev= 30
       0 3027.62    17.4 3025.42    40.3  3020.7    50.5 3019.61    81.5 3013.49
   118.1 3007.44   159.2 2996.89   214.4 2986.09     251 2985.12   255.6 2985.27
   264.7 2986.89   279.3 2984.78   305.5 2983.09   315.7 2981.31   320.8 2980.99
   349.4 2980.23   407.5 2981.19   421.7 2979.87   427.9 2979.36   433.2 2979.84
   439.7  2980.5   453.4 2980.15   470.1 2981.02   504.3 2983.97   528.1  2984.1
   572.6 2985.53   608.6 2985.73   628.7 2987.42   660.7 2987.23   697.7 2988.55
#Mann= 6 ,-1,0
       0      .1       0     260     .12       0   305.2     .08       0
   385.2     .12       0   421.7    .045       0   433.2     .12       0
Bank Sta=421.7,433.2
XS Rating Curve= 0 ,0
Exp/Cntr(USF)=0,0
Exp/Cntr=0.3,0.1

Type RM Length L Ch R = 1 ,1092    ,212.7,216.9,211.7
XS GIS Cut Line= 2
     2306903.908      600544.927     2306344.606      600128.917
#Sta/Elev= 30
       0 3058.25    26.4  3054.3    45.4 3049.23    68.2 3040.74      94 3033.63
   136.9 3015.89   154.2 3011.64   179.1  3003.9   222.6 2986.87   243.9 2980.28
   258.9 2978.47   303.8 2977.79   315.32976.027   321.3    2975   328.7 2976.01
   345.5 2977.09   368.2 2976.19   418.4 2976.53   433.4  2974.8   462.8  2977.2
   494.2  2982.4   542.5 2982.76   554.2 2983.96     560  2985.7   582.9 2996.86
   597.9 3001.91   632.8 2999.49   657.7 3000.05   683.2 2997.86   697.1  2997.7
#Mann= 9 ,-1,0
       0      .1       0      90     .12       0     210      .1       0
     240     .08       0   315.3    .045       0   328.7     .08       0
     330      .1       0     400     .08       0     450     .12       0
Bank Sta=315.3,328.7
XS Rating Curve= 0 ,0
Exp/Cntr=0.3,0.1

Type RM Length L Ch R = 1 ,876     ,246.2,249.5,247.4
XS GIS Cut Line= 2
2306961.25852852 600343.042094262306481.75320717600041.059869748
#Sta/Elev= 30
       0 3044.13      11 3040.09      41 3032.26    63.5 3024.95    76.9 3021.56
   108.6 3010.09   123.6 3003.05   143.1  2996.9   152.5 2991.95   161.7 2988.67
   168.6  2985.6   176.1  2983.7   184.9 2982.28   198.7 2981.64     240 2972.92
   247.1 2972.18   254.5    2973   263.2 2973.85   346.4  2976.3   422.7 2976.32
   445.6 2977.68   457.5  2980.4   469.9 2982.53   480.7 2983.99   502.4 2985.68
   511.8 2987.76   530.7 2994.18   535.4 2996.32   558.9    3010   566.7 3013.85
#Mann= 4 ,-1,0
       0      .1       0      30     .12       0     240    .045       0
   254.5     .12       0
Bank Sta=240,254.5
XS Rating Curve= 0 ,0
Exp/Cntr(USF)=0,0
Exp/Cntr=0.3,0.1

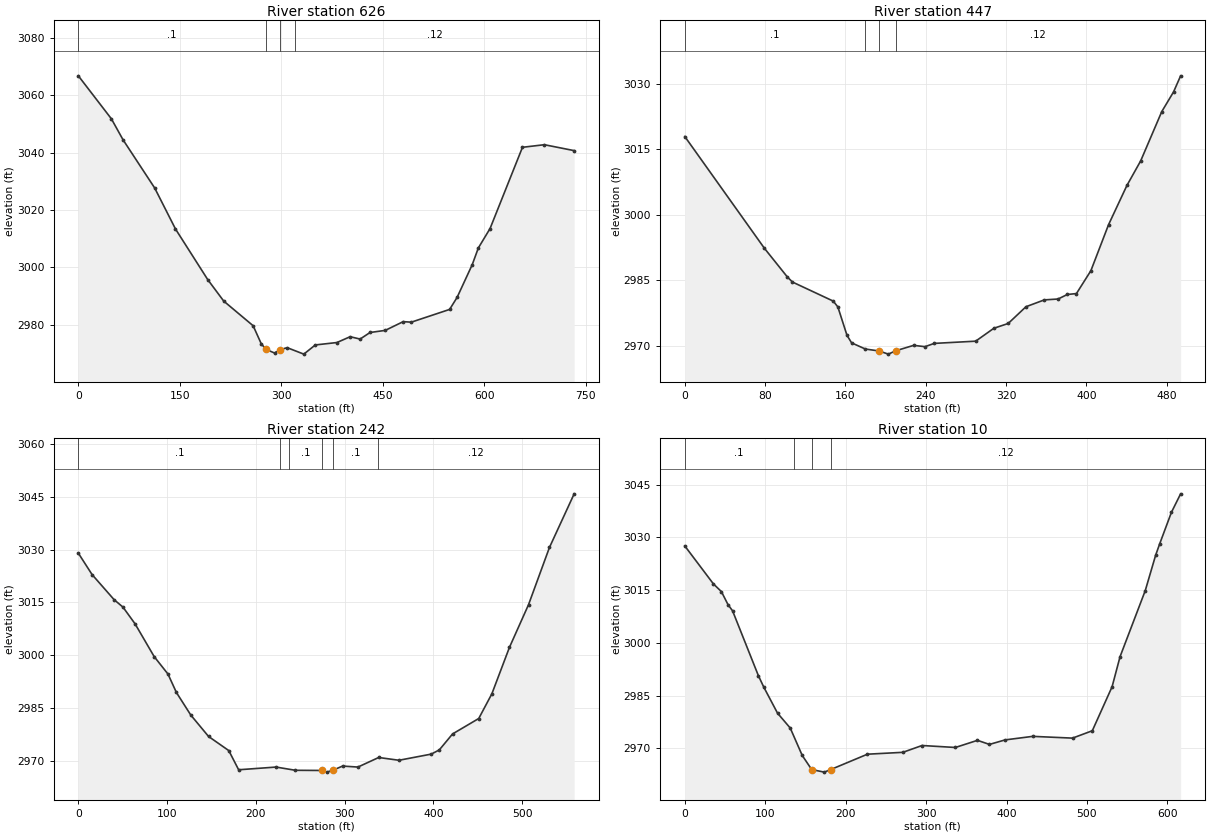
Type RM Length L Ch R = 1 ,626     ,180,179.1,176.2
XS GIS Cut Line= 2
     2307100.358      600205.185     2306501.765      599782.242
#Sta/Elev= 30
       0 3066.79    48.9 3051.79    66.1 3044.49   112.9 3027.68   143.6 3013.41
   191.2 2995.79   214.9 2988.28   258.4 2979.68   270.3 2973.44   277.3 2971.46
     290 2970.18   298.6 2971.39   308.8 2972.03   333.3 2969.79   350.3 2972.99
   382.2 2973.83   401.8 2975.86   416.5 2975.04   431.2 2977.33   453.6 2978.06
   480.2 2981.11   492.2 2980.93   548.8 2985.37   559.8 2989.53   582.3    3001
   591.3 3006.81   608.6 3013.57   656.5 3041.88   688.9 3042.78   732.9 3040.72
#Mann= 4 ,-1,0
       0      .1       0   277.3    .045       0   298.6      .1       0
     320     .12       0
Bank Sta=277.3,298.6
XS Rating Curve= 0 ,0
Exp/Cntr=0.3,0.1

Type RM Length L Ch R = 1 ,447     ,205.7,205.4,204.6
XS GIS Cut Line= 2
2307089.57685395599969.6647112372306657.34670513599730.394450282
#Sta/Elev= 30
       0 3017.95    79.3 2992.32   102.2 2985.73   107.3 2984.57   147.9  2980.2
   152.5 2978.87   161.6 2972.35   166.2 2970.62   179.9 2969.21   193.6 2968.76
   202.8 2968.04   210.3 2968.82     228 2970.05   239.3 2969.75   248.5  2970.5
   289.8 2971.01   307.9 2973.97   322.2 2975.07   339.9 2978.91   358.2 2980.48
   371.9 2980.68   381.1 2981.72   390.2 2981.93   404.6 2987.18   422.2 2997.73
   440.5 3006.73   454.2 3012.36   475.2 3023.66     487  3028.2     494 3031.87
#Mann= 4 ,-1,0
       0      .1       0     180     .12       0   193.6    .045       0
   210.3     .12       0
Bank Sta=193.6,210.3
XS Rating Curve= 0 ,0
Exp/Cntr(USF)=0,0
Exp/Cntr=0.3,0.1

Type RM Length L Ch R = 1 ,242     ,231.5,231.5,231.5
XS GIS Cut Line= 3
2307173.51440517599897.3047532872307042.30168142599723.640854206
2306742.68780505599560.952398318
#Sta/Elev= 30
       0 3028.97    15.5 3022.88    40.3 3015.75    50.3 3013.63    63.9 3008.89
    85.4 2999.59     101 2994.61   110.5 2989.37   126.7 2982.96   146.7 2976.88
   169.5 2972.86   180.6 2967.41   222.8 2968.18   244.6 2967.26   274.7 2967.21
     280 2966.74   286.5 2967.25   297.7 2968.46     315 2968.18   338.4  2970.9
   361.2 2970.11   397.6 2971.86   406.7 2973.06   421.6 2977.59   451.1 2981.98
   465.9    2989   485.7  3002.2   507.2 3014.33   530.8 3030.61   558.6 3045.83
#Mann= 6 ,-1,0
       0      .1       0  227.66     .12       0  237.66      .1       0
   274.7    .045       0   286.5      .1       0  337.66     .12       0
Bank Sta=274.7,286.5
XS Rating Curve= 0 ,0
Exp/Cntr=0.3,0.1

Type RM Length L Ch R = 1 ,10      ,,,
XS GIS Cut Line= 4
2307326.91751602599720.7464558882307243.94476424599640.668102423
2307085.71765619599637.7737041062306806.89061822599438.060220163
#Sta/Elev= 30
       0 3027.59    35.6 3016.79    45.5 3014.61    53.8 3010.87    59.4 3009.14
    91.5  2990.7    98.3  2987.4   115.3 2980.04   131.1 2975.81     146 2968.02
   157.8 2963.99   173.5 2963.27   181.4    2964   227.1 2968.37   271.1  2968.9
     295 2970.84   336.4 2970.28   363.9 2972.31   378.8 2971.15   398.2 2972.43
   432.6 2973.44   482.1 2972.94   506.7 2975.04   531.3 2987.56   541.2 2996.11
   572.5 3014.87   585.4 3024.92   590.4 3028.15   605.1 3037.17   616.5 3042.41
#Mann= 4 ,-1,0
       0      .1       0  135.31     .12       0   157.8    .045       0
   181.4     .12       0
Bank Sta=157.8,181.4
XS Rating Curve= 0 ,0
Exp/Cntr(USF)=0,0
Exp/Cntr=0.3,0.1
LCMann Table=0

Chan Stop Cuts=-1
Use User Specified Reach Order=0
Composite Channel Slope=5